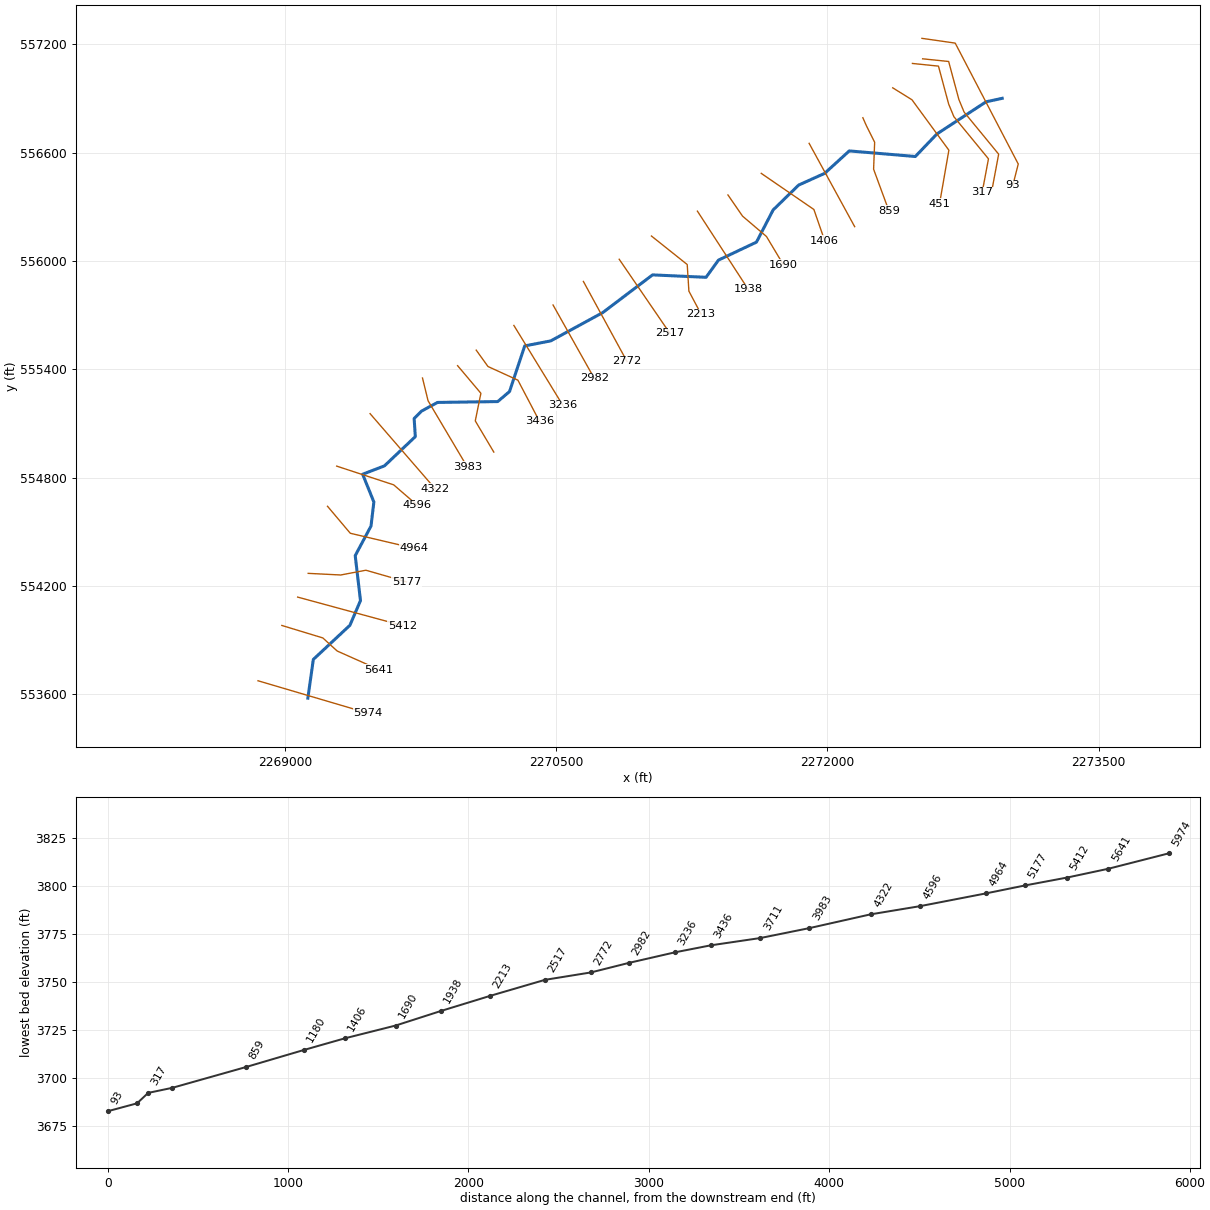
--- BEAVERCK.prj (project) ---

Proj Title=BEAVERCK
Current Plan=p01
Default Exp/Contr=0,0
English Units
Geom File=g01
Flow File=f01
Plan File=p01
BEGIN DESCRIPTION:
----------MODEL BY WOOD PLC 2022----------
AFH study
Randolph County, WV
HEC-RAS Version: RAS 6.2
Vertical Datum: NAVD88
Projection: NAD 1983 StatePlane West Virginia S FIPS 4702 (US Feet)
Terrain: 1-meter LIDAR (FEMA Region III 3DEP collected 2016-2018)
Land Use: 2019 NLCD
Hydrologic Method:
WV SIR2010-5033 regression equations
Additional Model Notes:
None
END DESCRIPTION:
DSS Export Rating Curves= 0
DSS Export Rating Curve Sorted= 0
DSS Export Volume Flow Curves= 0
DXF OffsetX= 0
DXF OffsetY= 0
DXF ScaleX= 0
DXF ScaleY= 0

--- BEAVERCK.p01 (plan) ---

Plan Title=Floodplain
Program Version=6.20
Short Identifier=Floodplain
Geom File=g01
Flow File=f01
Subcritical Flow
K Sum by GR= 0
Std Step Tol= 0.01
Critical Tol= 0.01
Num of Std Step Trials= 20
Max Error Tol= 0.3
Flow Tol Ratio= 0.001
Split Flow NTrial= 30
Split Flow Tol= 0.02
Split Flow Ratio= 0.02
Log Output Level= 0
Friction Slope Method= 1
Unsteady Friction Slope Method= 2
Unsteady Bridges Friction Slope Method= 1
Parabolic Critical Depth
Global Vel Dist= 0 , 0 , 0
Global Log Level= 0
CheckData=True
Encroach Param=-1 ,0,0, 0
Mapping Interval=1HOUR
Computation Time Step Use Courant=        0
Computation Time Step Use Time Series=    0
Computation Time Step Count To Double=0
Computation Time Step Max Doubling=0
Computation Time Step Max Halving=0
Computation Time Step Residence Courant=0
Run HTab= 0
Run UNet= 0
Run Sediment= 0
Run PostProcess= 0
Run WQNet= 0
Run RASMapper=-1
UNET Theta= 0
UNET Theta Warmup= 0
UNET ZTol= 0
UNET ZSATol= 0
UNET MxIter= 0
UNET Max Iter WO Improvement= 0
UNET MaxInSteps= 0
UNET DtIC= 0
UNET DtMin= 0
UNET MaxCRTS= 0
UNET WFStab= 0
UNET SFStab= 0
UNET WFX= 1
UNET SFX= 1
UNET Gravity=32.174
UNET 1D Methodology=Finite Difference
UNET DSS MLevel= 1
UNET Pardiso=0
UNET DZMax Abort= 0
UNET Use Existing IB Tables= 0
UNET Froude Reduction=False
UNET Froude Limit= 0
UNET Froude Power= 0
UNET D1 Cores= 0
UNET WindReference=Eulerian
UNET WindDragFormulation=Hsu (1988)
UNET D2 Coriolis=0
UNET D2 Cores= 0
UNET D2 Theta= 1
UNET D2 Theta Warmup= 1
UNET D2 Z Tol= 0.01
UNET D2 Volume Tol= 0.01
UNET D2 Max Iterations= 20
UNET D2 Equation= 0
UNET D2 RampUpFraction=0.1
UNET D2 TimeSlices= 1
UNET D2 Turbulence Formulation=Non-Conservative (original)
UNET D2 Eddy Viscosity=0.3
UNET D2 Transverse Eddy Viscosity=0.1
UNET D2 Smagorinsky Mixing=0
UNET D2 BCVolumeCheck=0
UNET D2 Cores=0
UNET D2 SolverType=PARDISO (Direct)
UNET D2 Minimum Iterations= 2147483647
UNET D2 Maximum Iterations= 2147483647
UNET D2 Restart Number= 10
UNET D2 Relaxation Coeff=1.3
UNET D2 SOR Precondition Iterations= 10
UNET D2 ILUT Maximum Fill= 8
UNET D2 ILUT Tolerance=1E-08
UNET D1D2 MaxIter= 0
UNET D1D2 ZTol=0.01
UNET D1D2 QTol=0.1
UNET D1D2 MinQTol=1
Write IC File= 0
Write IC File at Fixed DateTime=0
Write IC File at Sim End=0
Echo Input=False
Echo Parameters=False
Echo Output=False
Write Detailed= 0
HDF Write Warmup=0
HDF Write Time Slices=0
HDF Flush=0
HDF Compression= 1
HDF Chunk Size= 1
HDF Spatial Parts= 1
HDF Use Max Rows=0
HDF Fixed Rows= 1
Calibration Method= 0
Calibration Iterations= 20
Calibration Max Change=0.05
Calibration Tolerance=0.2
Calibration Maximum=1.5
Calibration Minimum=0.5
Calibration Optimization Method= 1
WQ AD Non Conservative
WQ ULTIMATE=-1
WQ Max Comp Step=1HOUR
WQ Output Interval=15MIN
WQ Output Selected Increments= 0
WQ Output face flow=0
WQ Output face velocity=0
WQ Output face area=0
WQ Output face dispersion=0
WQ Output cell volume=0
WQ Output cell surface area=0
WQ Output cell continuity=0
WQ Output cumulative cell continuity=0
WQ Output face conc=0
WQ Output face dconc_dx=0
WQ Output face courant=0
WQ Output face peclet=0
WQ Output face adv mass=0
WQ Output face disp mass=0
WQ Output cell mass=0
WQ Output cell source sink temp=0
WQ Output nsm pathways=0
WQ Output nsm derived pathways=0
WQ Create Restart=0
WQ Fixed Restart=0
WQ System Summary=0
WQ Write To DSS=0
Sorting and Armoring Iterations= 10
XS Update Threshold= 0.02
Bed Roughness Predictor= 0
Hydraulics Update Threshold= 0.02
Energy Slope Method= 1
Volume Change Method= 1
Sediment Retention Method= 0
Sediment TS Multiplier= 1
Warm Up Method= 0
XS Weighting Method= 0
Number of US Weighted Cross Sections= 1
Number of DS Weighted Cross Sections= 1
Upstream XS Weight=0
Main XS Weight=1
Downstream XS Weight=0
Number of DS XS's Weighted with US Boundary= 1
Upstream Boundary Weight= 1
Weight of XSs Associated with US Boundary= 0
Number of US XS's Weighted with DS Boundary= 1
Downstream Boundary Weight= 0.5
Weight of XSs Associated with DS Boundary= 0.5
Percentile Method= 0
Sediment Output Level= 3
Mass or Volume Output= 0
Output Increment Type= 1
Profile and TS Output Increment= 1
Transport Output Increment 1
XS Output Flag= 0
XS Output Increment= 10
Read HDF5 Sediment Hotstart= 0
Sediment Hotstart Type= 0
Write Gradation File= 0
Read Gradation Hotstart= 0
Write HDF5 File= 1
Write Binary Output= 1
Write DSS Sediment File= 0
DSS Sediment Output Type= 1
SV Curve= 0
Specific Gage Flag= 0
Subcell Erosion Methods= 0
Subcell Deposition Methods= 0
Advection Scheme= 1
Matrix Solver= 0
Implicit Weighting Factor= 1
Maximum Outer Loop Convergence Iterations= 5
Convergence Maximum Absolute= 0.001
Convergence RMSE= 0.0001
Grain Fractions Max Abs Error= 0.001
Max Subgrid Regions= 1
Max Subgrid Length Scale= 3.402823E+38
Initial Layer Thickness= 3.402823E+38
Min Layer Thickness= 3.402823E+38
Max Layer Thickness= 3.402823E+38
Number of Layers= 5

--- BEAVERCK.f01 (steady flow) ---

Flow Title=Flow
Program Version=6.20
Number of Profiles= 1
Profile Names=P100yr
River Rch & RM=BEAVERCK,Main            ,5974
     366
River Rch & RM=BEAVERCK,Main            ,3711
     413
River Rch & RM=BEAVERCK,Main            ,1938
     459
Boundary for River Rch & Prof#=BEAVERCK,Main            , 1
Up Type= 0
Dn Type= 3
Dn Slope=0.03495
DSS Import GetInterval= 0
DSS Import GetPeak= 0
DSS Import FillOption= 0

--- BEAVERCK.g01 (geometry) ---

Geom Title=Geometry
Program Version=6.20

River Reach=BEAVERCK        ,Main
Reach XY= 30
      2269126.12      553578.524     2269156.275      553792.892
     2269358.755      553982.062     2269417.192      554118.764
     2269388.083      554368.006     2269475.483      554531.909
     2269491.259      554665.1212269429.15538752554819.012078405
     2269549.731      554865.255     2269720.535      555027.291
     2269714.046      555127.757     2269754.823      555168.596
     2269843.148      555216.773     2270176.482      555221.548
     2270241.894      555277.508     2270325.708       555529.93
      2270469.73      555557.724     2270757.428      555714.603
     2271032.834      555923.387     2271328.678      555910.024
     2271397.456      556005.214     2271607.644      556104.891
      2271699.68      556282.919     2271840.956       556420.94
     2271984.837      556485.827     2272120.904      556610.176
     2272486.356      556579.317     2272605.843      556704.143
     2272877.892      556882.442     2272966.899      556901.482

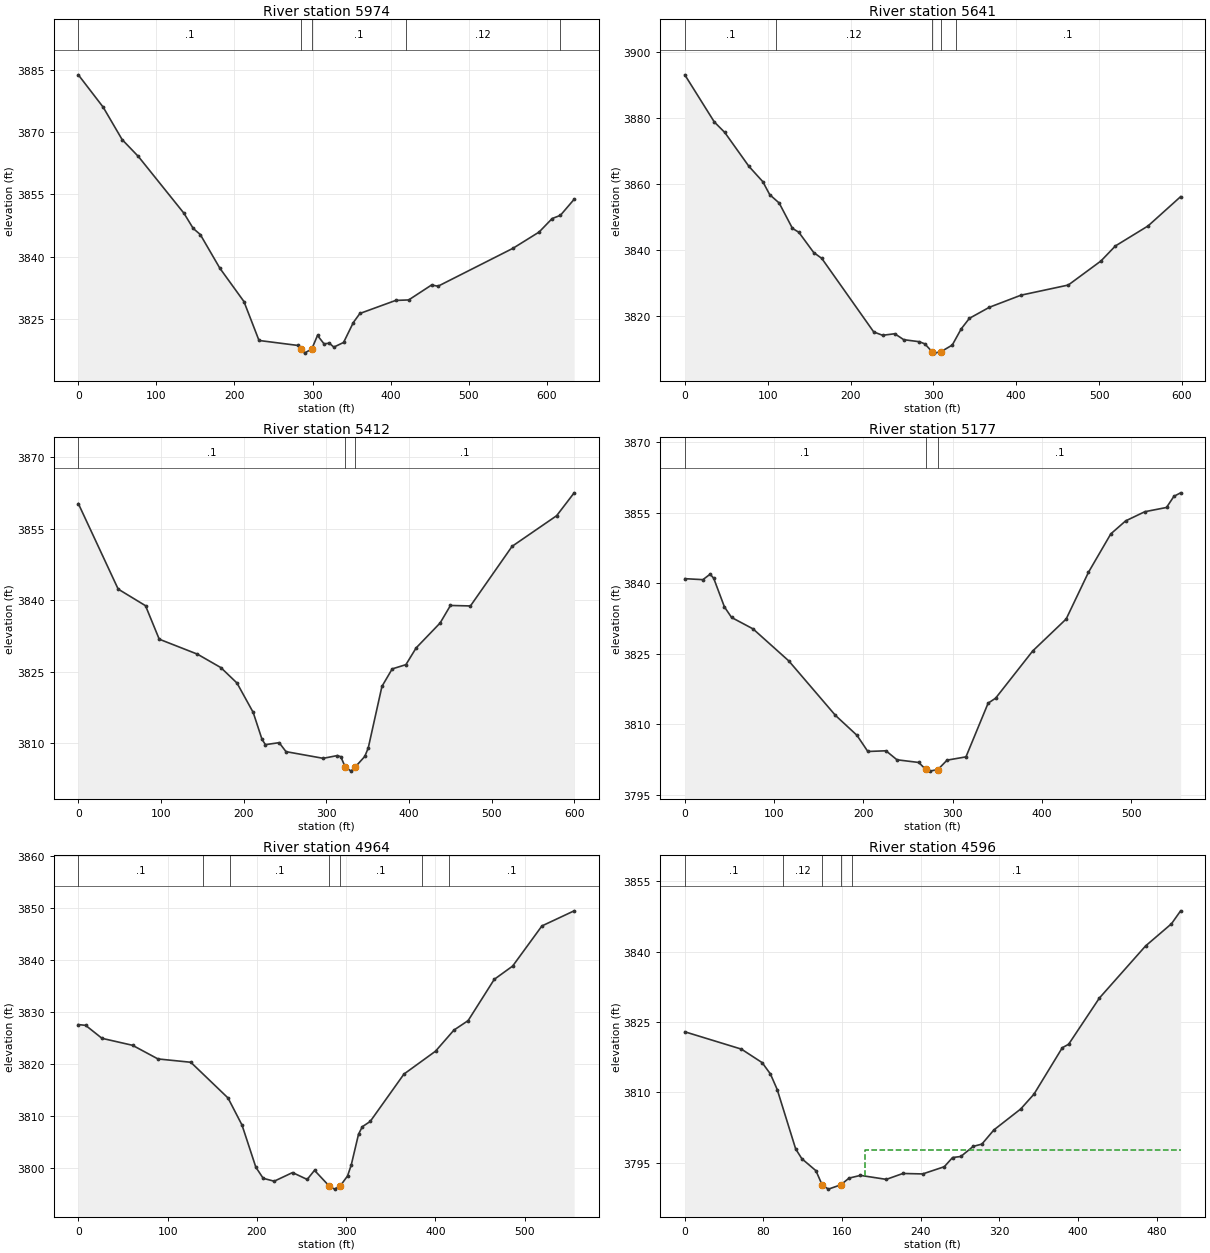
Type RM Length L Ch R = 1 ,5974    ,335.8,333.4,330.7
XS GIS Cut Line= 3
2268850.38063325553674.8532168542269355.37755641553525.664020173
 2269459.0895484553494.160715711
#Sta/Elev= 30
       0 3883.83    31.8 3876.04    56.1 3868.22    76.9 3864.15   135.3 3850.46
   147.1 3846.82   156.2 3845.34   181.2 3837.24   212.1 3829.19   231.4 3819.81
   281.3 3818.61   285.5 3817.72   289.7 3816.76     299 3817.78   306.3 3821.02
   314.7 3818.99   321.5 3819.16   327.2 3818.21   339.7 3819.33   352.2 3824.14
   360.6 3826.32   406.4 3829.46   423.1 3829.58   452.3 3833.17   460.7 3832.89
   556.7 3842.03   590.1 3845.94   606.8 3849.19   617.4 3849.97     635 3853.84
#Mann= 5 ,-1,0
       0      .1       0   285.5    .045       0     299      .1       0
     420     .12       0  616.57      .1       0
Bank Sta=285.5,299
XS Rating Curve= 0 ,0
Exp/Cntr=0.3,0.1

Type RM Length L Ch R = 1 ,5641    ,225.3,228.9,231.1
XS GIS Cut Line= 4
2268982.09755573553981.2846988062269208.86119994553912.171209435
2269288.24695194553839.6885663042269520.00494211553736.181757982
#Sta/Elev= 30
       0  3893.2    35.6 3878.91    48.2 3875.73    77.4 3865.44    94.2 3860.78
   102.5 3856.85   113.9 3854.32   129.9 3846.64   137.6 3845.45   155.6 3839.29
   165.3 3837.53     228 3815.22   238.7  3814.2   253.4 3814.67   264.2 3812.87
     283 3812.25   289.7  3811.6   298.2 3809.28     301 3808.79   309.5 3809.27
   322.8 3811.24   333.6 3816.15   343.5 3819.35   367.6  3822.7   405.8 3826.37
   462.8 3829.44   502.2 3836.73   519.7  3841.3   559.1 3847.37   598.4 3856.25
#Mann= 5 ,-1,0
       0      .1       0     110     .12       0   298.2    .045       0
   309.5     .12       0  327.06      .1       0
Bank Sta=298.2,309.5
XS Rating Curve= 0 ,0
Exp/Cntr(USF)=0,0
Exp/Cntr=0.3,0.1

Type RM Length L Ch R = 1 ,5412    ,231.6,234.6,237.5
XS GIS Cut Line= 2
2269069.69580013554138.3738319812269648.64499058553980.837058876
#Sta/Elev= 30
       0 3860.22    48.2 3842.32    81.3 3838.84    97.9 3831.83   144.2 3828.69
   172.5 3825.88     192 3822.65   211.6  3816.5   222.3 3810.85   226.4 3809.75
     243 3810.17   251.3 3808.29   296.3 3806.89   313.5 3807.47   317.6 3807.22
  322.953805.087   330.1 3804.21   335.4 3805.14   346.6 3807.28   350.8 3809.04
   367.4 3821.95   379.8 3825.61   396.4  3826.5   408.8 3830.01   437.8 3835.22
   450.3 3838.89   474.5 3838.79   524.9 3851.27   578.8 3857.68     600 3862.47
#Mann= 3 ,-1,0
       0      .1       0  322.95    .045       0   335.4      .1       0
Bank Sta=322.95,335.4
XS Rating Curve= 0 ,0
Exp/Cntr(USF)=0,0
Exp/Cntr=0.3,0.1

Type RM Length L Ch R = 1 ,5177    ,215.3,213.8,209.4
XS GIS Cut Line= 4
2269127.85620018554269.897128944 2269307.8057604554260.778207351
2269447.01845594554287.240124685 2269671.3694942554222.811108568
#Sta/Elev= 30
       0 3840.96    20.3 3840.75    28.4 3841.92    32.4 3841.03    44.4 3834.96
    52.4 3832.72    76.4  3830.3   116.5 3823.49   168.7 3811.93   192.8  3807.7
     205 3804.26   225.3 3804.41   237.6  3802.5     262 3801.93269.74443800.474
   274.2 3800.09283.4444 3800.42   293.7 3802.42   314.9 3803.12   339.7 3814.52
   348.1 3815.58   389.7 3825.62   427.1 3832.39   452.1 3842.32   477.1 3850.47
   493.7 3853.23   515.2 3855.18   539.5 3856.08   547.8 3858.45   555.3 3859.19
#Mann= 3 ,-1,0
       0      .1       0269.7444    .045       0283.4444      .1       0
Bank Sta=269.7444,283.4444
XS Rating Curve= 0 ,0
Exp/Cntr(USF)=0,0
Exp/Cntr=0.3,0.1

Type RM Length L Ch R = 1 ,4964    ,369.1,368.1,365.5
XS GIS Cut Line= 3
2269234.89060158554641.4385300332269360.72959507554492.032354484
2269711.26196294554409.448632747
#Sta/Elev= 30
       0 3827.62     8.2 3827.47    26.5 3824.98    60.7 3823.64    89.2 3821.02
     126 3820.38   167.7 3813.52   183.4 3808.31   198.9 3800.21   207.1 3798.09
   219.4 3797.53     240 3799.19   256.4 3797.87   264.6 3799.62   281.1  3796.6
   287.1 3796.01   293.4 3796.62   301.6 3798.54   305.7 3800.61   313.9 3806.55
   318.1 3807.99     327 3809.01   364.8 3818.11   400.2 3822.51   420.8 3826.56
   436.7 3828.38     466 3836.31   486.6 3838.86   519.4 3846.57   555.5 3849.47
#Mann= 7 ,-1,0
       0      .1       0     140     .12       0     170      .1       0
   281.1    .045       0   293.4      .1       0  385.34     .12       0
  415.34      .1       0
Bank Sta=281.1,293.4
XS Rating Curve= 0 ,0
Exp/Cntr(USF)=0,0
Exp/Cntr=0.3,0.1

Type RM Length L Ch R = 1 ,4596    ,279,273.6,268.5
XS GIS Cut Line= 3
2269285.44021854 554864.027198442269601.18788736554760.103082255
2269731.15917235554647.490368684
#Sta/Elev= 30
       0 3822.89    57.6 3819.19    78.7 3816.31    87.1 3813.89      94 3810.58
   112.8  3797.9   119.1 3795.81   133.4 3793.26  139.753790.217   146.1 3789.33
   158.7 3790.25   167.1 3791.68   178.7 3792.26     205 3791.41   221.9 3792.67
     242 3792.57     264 3794.11   272.4 3796.07   280.8 3796.29   293.4 3798.45
   302.2 3798.93   314.5 3801.97   341.7 3806.42   355.2 3809.58     384 3819.48
   390.5 3820.24   421.7 3830.07   468.7 3841.19   495.1 3845.93   504.4 3848.69
#Mann= 5 ,-1,0
       0      .1       0     100     .12       0  139.75    .045       0
   158.7     .12       0     170      .1       0
#XS Ineff= 2 , 0
                          183.25         3797.62
Permanent Ineff=
       F       F
Bank Sta=139.75,158.7
XS Rating Curve= 0 ,0
Exp/Cntr(USF)=0,0
Exp/Cntr=0.3,0.1

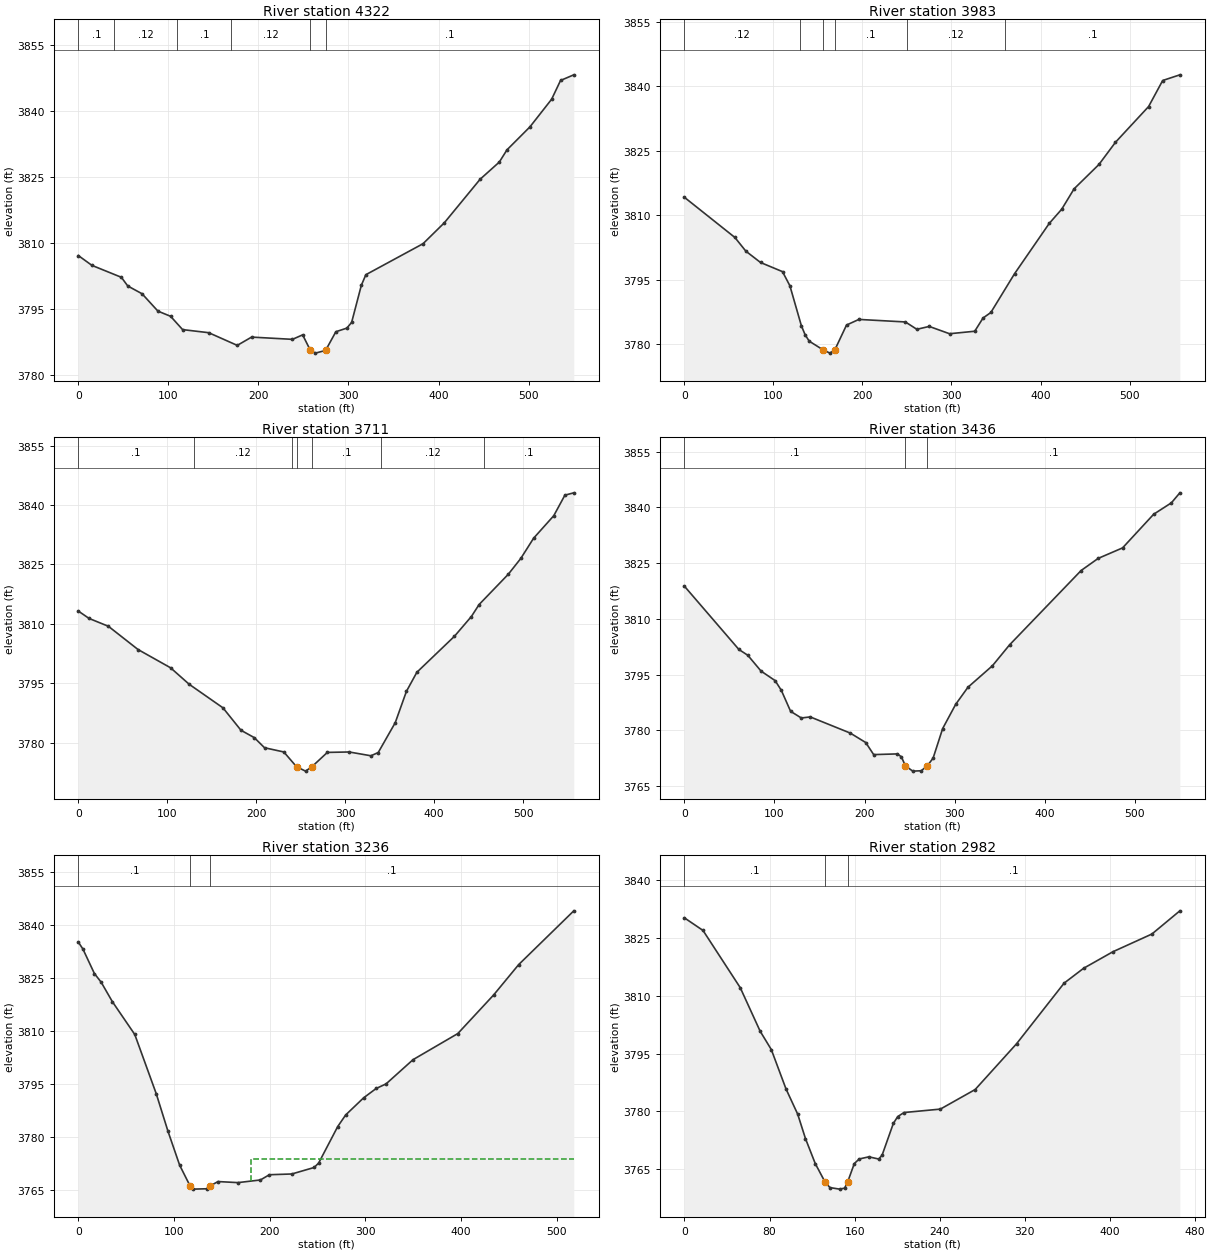
Type RM Length L Ch R = 1 ,4322    ,337.7,338.7,336.4
XS GIS Cut Line= 2
 2269470.3217449  555154.6915424 2269830.2548624 554738.54385418
#Sta/Elev= 30
       0 3807.24    15.1 3805.01    47.8  3802.3    54.9 3800.33    70.8 3798.56
    88.4 3794.62   102.5 3793.44   115.8 3790.42   144.8 3789.72   176.5 3786.84
   192.4 3788.72   237.8 3788.21   249.1 3789.23   257.6 3785.75   263.3 3785.08
   274.6  3785.7     286 3789.94   298.2 3790.76   303.5 3792.06   314.3 3800.49
   319.3 3802.89   382.8 3809.93   406.4 3814.67   446.2 3824.57   467.5 3828.47
     476 3831.24   501.5 3836.46   525.6 3842.74   535.5    3847   550.2 3848.28
#Mann= 6 ,-1,0
       0      .1       0      40     .12       0     110      .1       0
     170     .12       0   257.6    .045       0   274.6      .1       0
Bank Sta=257.6,274.6
XS Rating Curve= 0 ,0
Exp/Cntr(USF)=0,0
Exp/Cntr=0.3,0.1

Type RM Length L Ch R = 1 ,3983    ,277,272.3,266.3
XS GIS Cut Line= 3
2269760.21316975555352.2498691932269791.02338128555226.062930955
2270008.30227707554858.967699531
#Sta/Elev= 30
       0 3814.18    56.7 3804.84      69 3801.66    85.5 3799.02   110.2 3796.89
   118.5  3793.6   131.4  3784.3   135.6 3782.21   140.2 3780.72   155.7 3778.71
   163.5 3777.94  169.063778.738   182.1 3784.47     196 3785.78   248.2 3785.19
   261.1 3783.48     275 3784.15   297.8 3782.45   326.1 3783.03   335.4  3786.1
   344.2 3787.39   370.8  3796.4   409.8 3808.11   423.8 3811.41   437.7 3816.15
   465.6 3821.81   484.2 3826.98   521.4 3835.29   537.2 3841.34   556.5 3842.66
#Mann= 6 ,-1,0
       0     .12       0  129.89      .1       0   155.7    .045       0
  169.06      .1       0  249.89     .12       0  359.89      .1       0
Bank Sta=155.7,169.06
XS Rating Curve= 0 ,0
Exp/Cntr(USF)=0,0
Exp/Cntr=0.3,0.1

Type RM Length L Ch R = 1 ,3711    ,260.9,274.6,286.7
XS GIS Cut Line= 4
2269954.39695786 555420.500497452270083.25499009555267.481584173
2270052.19100018555114.4626708962270154.58711508554941.884949155
#Sta/Elev= 30
       0 3813.23    12.1 3811.36    33.8 3809.38    67.1 3803.51   103.7 3798.89
   124.6 3794.73   162.6 3788.77   182.8 3783.11   197.8 3781.24   209.3 3778.69
     231 3777.62   245.3 3773.88   255.4 3772.78   262.3 3773.84   279.9 3777.51
   304.4 3777.62   328.9 3776.66   337.1 3777.48   356.2 3785.01   368.8 3792.94
   380.5 3797.75   422.8 3806.86   441.8 3811.85   450.5 3814.88   483.3 3822.53
   497.3 3826.51   511.8 3831.65   534.4 3837.32   546.9 3842.51   556.9  3843.1
#Mann= 7 ,-1,0
       0      .1       0     130     .12       0  240.05      .1       0
   245.3    .045       0   262.3      .1       0  340.05     .12       0
  456.19      .1       0
Bank Sta=245.3,262.3
XS Rating Curve= 0 ,0
Exp/Cntr(USF)=0,0
Exp/Cntr=0.3,0.1

Type RM Length L Ch R = 1 ,3436    ,207,200.7,195.3
XS GIS Cut Line= 4
2270057.49754109555506.3718722122270122.37260702 555415.89842487
2270288.04721989555339.9642273042270407.01813536 555112.85710022
#Sta/Elev= 30
       0  3818.8    60.5 3801.75    70.4 3800.19    85.1 3795.93   100.7 3793.37
   107.6 3790.75   117.9  3785.1   129.8  3783.3   139.7 3783.59   184.1 3779.24
   201.3 3776.69   210.1 3773.44   236.5 3773.63   240.9 3772.83   245.3 3770.42
   253.5 3768.99   262.9 3769.09  269.763770.448   276.1  3772.5   286.7 3780.46
   301.2    3787   314.8 3791.59   341.9 3797.36   360.9 3802.98   440.4 3823.02
   459.3 3826.28   486.4 3829.11   520.9 3838.17   540.6 3841.25     550 3843.94
#Mann= 3 ,-1,0
       0      .1       0   245.3    .045       0  269.76      .1       0
Bank Sta=245.3,269.76
XS Rating Curve= 0 ,0
Exp/Cntr(USF)=0,0
Exp/Cntr=0.3,0.1

Type RM Length L Ch R = 1 ,3236    ,253.4,253.9,252.9
XS GIS Cut Line= 2
2270265.67634899555643.4810170752270535.96219313555201.770450924
#Sta/Elev= 30
       0 3835.13     4.8 3833.18    16.8 3826.25    23.9 3823.79    35.5 3818.33
      59 3809.02    81.4 3792.31    93.7 3781.67   105.9 3772.08     117  3766.1
   119.9 3765.31     134 3765.41   137.3 3766.16     146 3767.45   166.8 3767.15
   190.3  3767.9   199.7 3769.38   223.1 3769.59   246.5 3771.43   251.2  3772.7
   271.1    3783   279.4 3786.27   298.1  3791.1   311.3 3793.76   321.6 3795.05
   349.8  3801.9   396.6 3809.28     434 3820.18   460.2 3828.77   517.8 3843.97
#Mann= 3 ,-1,0
       0      .1       0     117    .045       0   137.3      .1       0
#XS Ineff= 2 , 0
                          180.27         3773.92
Permanent Ineff=
       F       F
Bank Sta=117,137.3
XS Rating Curve= 0 ,0
Exp/Cntr(USF)=0,0
Exp/Cntr=0.3,0.1

Type RM Length L Ch R = 1 ,2982    ,209.8,209.6,209.3
XS GIS Cut Line= 2
2270482.48478639555756.4517957722270710.28737908555350.318890608
#Sta/Elev= 30
       0 3830.23    17.5 3826.96    52.5 3812.11    71.2 3800.82    81.7 3796.05
    95.5 3785.85   106.5 3779.29   113.8 3772.96     123 3766.48   132.2 3761.69
   136.8 3760.25   145.9 3759.85   150.6 3760.11   153.5 3761.75   159.7 3766.48
   164.3 3767.67   173.4 3768.23   182.6 3767.66   185.8 3768.64   196.4  3776.9
   200.5 3778.67   206.4 3779.72   240.6 3780.61   273.3 3785.69   312.2 3797.56
   356.9 3813.29   375.2 3817.14   402.8 3821.44   439.4 3826.03   465.7 3832.05
#Mann= 3 ,-1,0
       0      .1       0   132.2    .045       0   153.5      .1       0
Bank Sta=132.2,153.5
XS Rating Curve= 0 ,0
Exp/Cntr(USF)=0,0
Exp/Cntr=0.3,0.1

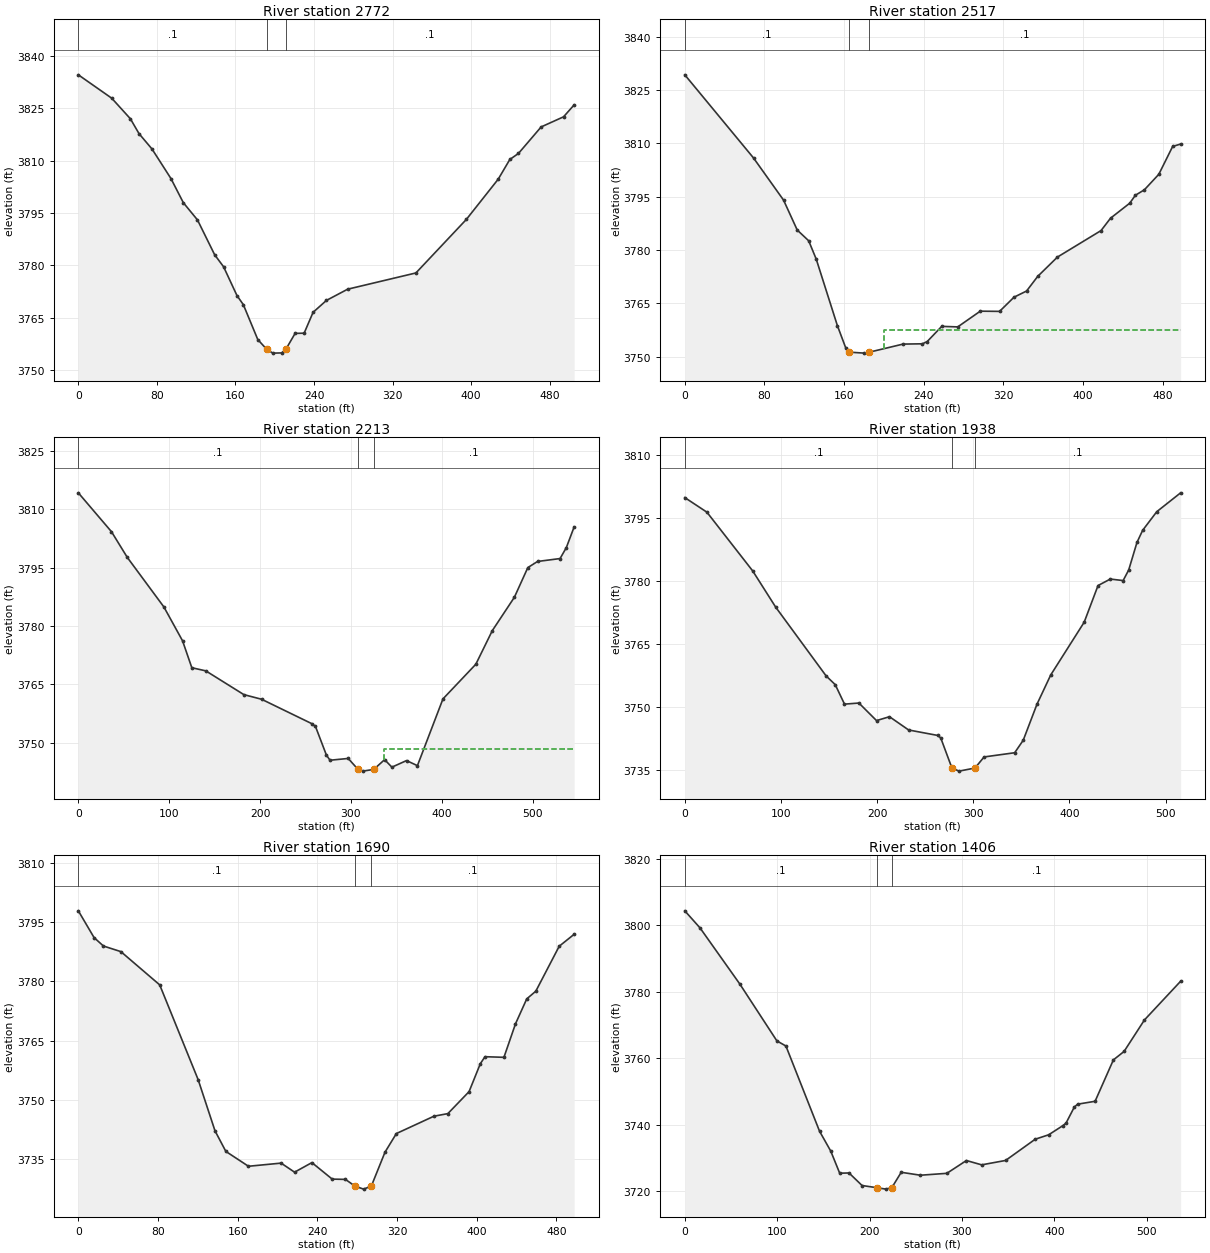
Type RM Length L Ch R = 1 ,2772    ,253.7,255.3,255.7
XS GIS Cut Line= 2
2270650.19626347555887.0632957372270891.50954561555443.700183877
#Sta/Elev= 30
       0 3834.57      34 3827.88      53 3821.99    61.8 3817.73      75 3813.34
    94.3 3804.88   106.9 3797.97   121.3 3793.04   138.8 3783.06   147.9 3779.62
   161.5 3771.39     168 3768.78   182.7  3758.8   191.6 3756.06     198 3754.91
   207.1 3754.97   211.6 3756.16   220.7 3760.56   229.9 3760.62     239 3766.59
   252.6    3770   274.2 3773.21   343.7 3777.86   395.1  3793.2   427.5 3804.71
   439.3 3810.34   448.1 3812.07   471.2 3819.66     494 3822.55   504.8 3825.97
#Mann= 3 ,-1,0
       0      .1       0   191.6    .045       0   211.6      .1       0
Bank Sta=191.6,211.6
XS Rating Curve= 0 ,0
Exp/Cntr(USF)=0,0
Exp/Cntr=0.3,0.1

Type RM Length L Ch R = 1 ,2517    ,307.2,304,296.1
XS GIS Cut Line= 2
2270848.21466684556010.152476807 2271129.1873357555599.049887419
#Sta/Elev= 30
       0 3829.25      69 3805.89    99.2 3794.03   112.9 3785.64   124.4 3782.62
     132 3777.45   153.2  3758.8   161.8 3752.38   164.7 3751.33   180.4 3751.05
   185.3 3751.32   219.2 3753.59   238.6 3753.67   243.4  3754.3     258 3758.57
   274.1 3758.42   296.7 3762.84   316.1 3762.78   330.6 3766.77   343.2  3768.5
   354.4 3772.62   374.2 3778.04     418 3785.49   427.5 3788.96   446.8 3793.18
   452.5 3795.42   461.5 3796.94     476  3801.3   489.9 3809.13   497.9  3809.8
#Mann= 3 ,-1,0
       0      .1       0   164.7    .045       0   185.3      .1       0
#XS Ineff= 2 , 0
                          200.02          3757.5
Permanent Ineff=
       F       F
Bank Sta=164.7,185.3
XS Rating Curve= 0 ,0
Exp/Cntr(USF)=0,0
Exp/Cntr=0.3,0.1

Type RM Length L Ch R = 1 ,2213    ,270.9,274.8,279.2
XS GIS Cut Line= 4
2271026.52436098556138.7848657922271224.56898987555980.802834035
2271233.77313503555833.5365114822271301.48400507 555705.53469855
#Sta/Elev= 30
       0 3814.28    36.5 3804.28    53.9 3797.67    94.2 3784.92   114.7 3776.23
   124.9 3769.31   140.3  3768.5   182.2 3762.39   201.7  3761.2     257 3754.92
     261 3754.21     273 3746.86     277 3745.52     297 3745.98  307.883743.158
     313 3742.72   325.1 3743.16   337.1 3745.67   345.1 3743.74   361.2 3745.43
   373.2 3744.13   401.3 3761.29   437.5 3770.21   455.6 3778.84   479.9 3787.42
   494.7 3795.05   505.4 3796.63   530.2 3797.38   537.1  3800.2   545.7 3805.53
#Mann= 3 ,-1,0
       0      .1       0  307.88    .045       0   325.1      .1       0
#XS Ineff= 2 , 0
                           336.6         3748.42
Permanent Ineff=
       F       F
Bank Sta=307.88,325.1
XS Rating Curve= 0 ,0
Exp/Cntr(USF)=0,0
Exp/Cntr=0.3,0.1

Type RM Length L Ch R = 1 ,1938    ,245.3,248.4,249.2
XS GIS Cut Line= 2
2271280.94437897556276.4859972842271561.67080634555843.891174787
#Sta/Elev= 30
       0 3799.81      23 3796.34    70.7 3782.36    94.5 3773.79     147 3757.43
   156.5 3755.35   166.1 3750.73   181.1 3750.99   199.4 3746.82   212.9 3747.74
   232.8 3744.59   263.1 3743.29   266.2  3742.7   277.8 3735.57   285.2 3734.81
  301.823735.546   311.3 3738.18   343.1 3739.18     352 3742.15   366.3 3750.71
   380.6 3757.66   415.4  3770.2   429.8 3778.91   442.6 3780.45   455.9 3780.09
   461.7 3782.61   470.3 3789.16   476.2 3792.03   490.9 3796.46   515.7 3800.94
#Mann= 3 ,-1,0
       0      .1       0   277.8    .045       0  301.82      .1       0
Bank Sta=277.8,301.82
XS Rating Curve= 0 ,0
Exp/Cntr(USF)=0,0
Exp/Cntr=0.3,0.1

Type RM Length L Ch R = 1 ,1690    ,282.5,283.4,284
XS GIS Cut Line= 4
2271449.88065331556366.2366413962271530.60681642556248.873561805
2271662.91640309556136.1227836012271756.09012727555980.365268358
#Sta/Elev= 30
       0 3797.93    15.8 3791.14    25.2    3789    42.7 3787.58    81.7 3779.14
   120.3 3755.09   137.2 3742.12   148.1 3736.89   170.8 3733.12   203.6 3733.92
   217.1 3731.62   234.5 3734.05   254.9 3729.86   268.2 3729.79   277.6  3728.1
   286.4 3727.32  294.143728.068   307.9  3736.7   319.3 3741.42     357 3745.82
     371 3746.48   392.3 3752.06   403.6 3759.15   408.3 3760.92   427.3 3760.76
   438.9 3769.26   450.2 3775.59   459.3 3777.54   482.8 3788.95   497.8 3791.98
#Mann= 3 ,-1,0
       0      .1       0   277.6    .045       0  294.14      .1       0
Bank Sta=277.6,294.14
XS Rating Curve= 0 ,0
Exp/Cntr(USF)=0,0
Exp/Cntr=0.3,0.1

Type RM Length L Ch R = 1 ,1406    ,228.7,226.8,220.2
XS GIS Cut Line= 3
2271633.96985658556485.8694384832271925.23454014556285.690142444
 2271985.2081719556112.437729824
#Sta/Elev= 30
       0  3804.3    16.5 3799.16    59.6 3782.28    99.7  3765.2   109.5 3763.65
   145.9 3738.03     158 3732.07   167.7 3725.42   177.8 3725.49   191.9 3721.72
   207.6 3721.07   217.8 3720.63  224.213721.107   234.3 3725.69   255.1 3724.81
   283.7 3725.38   304.9 3729.23   321.4 3727.93   347.3 3729.25   379.4 3735.64
   393.9 3736.96     409 3739.66   412.7 3740.46   421.7  3745.3   425.3 3746.17
   444.2 3747.04     464 3759.48   475.6 3762.03   497.6 3771.48   536.8 3783.13
#Mann= 3 ,-1,0
       0      .1       0   207.6    .045       0  224.21      .1       0
Bank Sta=207.6,224.21
XS Rating Curve= 0 ,0
Exp/Cntr(USF)=0,0
Exp/Cntr=0.3,0.1

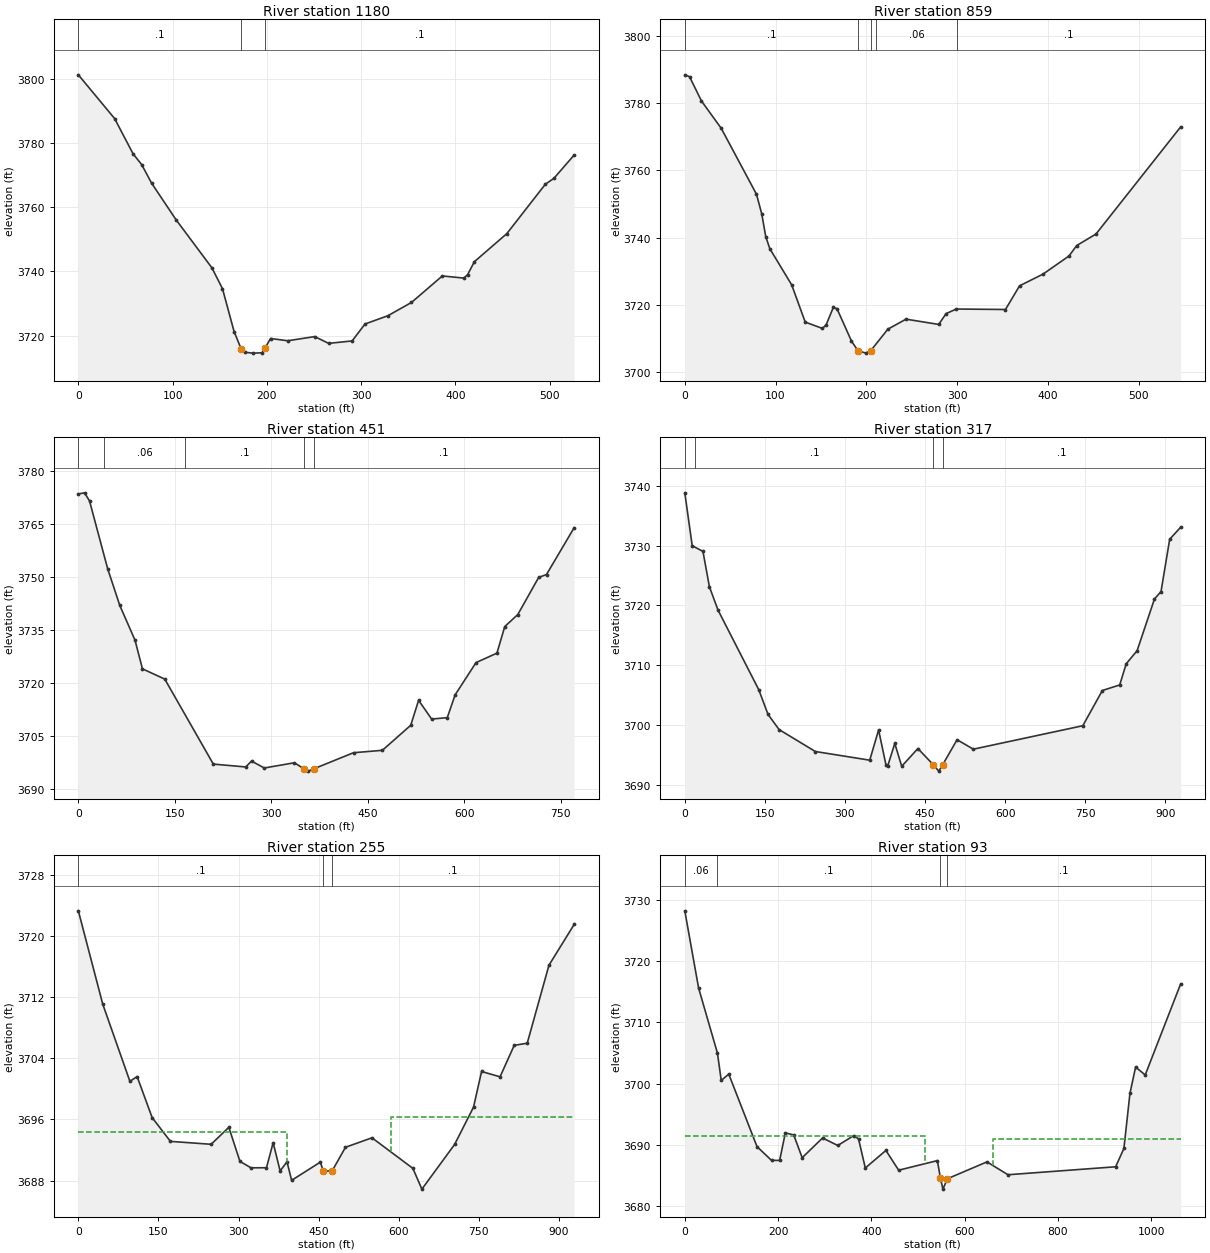
Type RM Length L Ch R = 1 ,1180    ,324.3,320.7,316.4
XS GIS Cut Line= 2
2271898.93829877556652.1422763212272150.83645249556190.495868919
#Sta/Elev= 30
       0 3801.15    38.5 3787.54    58.1 3776.56    67.2 3773.22    77.7 3767.46
   103.6 3756.09   141.7  3741.1   152.9 3734.62   165.2 3721.29  172.523716.014
   176.5 3714.84   185.6 3714.58   194.7 3714.68   197.7 3716.03   203.9 3719.13
   222.1 3718.43   250.7 3719.72   265.5 3717.62   290.4 3718.37   304.1 3723.65
   328.3 3726.21   353.3 3730.33   386.1 3738.59   408.9 3737.92   412.9 3738.99
   420.1 3743.03   454.5 3751.76   495.4 3767.14   504.3 3768.91   525.9  3776.2
#Mann= 3 ,-1,0
       0      .1       0  172.52    .045       0   197.7      .1       0
Bank Sta=172.52,197.7
XS Rating Curve= 0 ,0
Exp/Cntr(USF)=0,0
Exp/Cntr=0.3,0.1

Type RM Length L Ch R = 1 ,859     ,401.8,407.7,411.7
XS GIS Cut Line= 5
2272196.07646257556793.9740910582272216.44529089556748.097157694
2272261.31549854556658.3567423882272255.56290782556508.789383546
2272340.46172141556277.744801603
#Sta/Elev= 30
       0 3788.33     5.2 3787.78    18.4 3780.55    40.1 3772.47      79 3752.88
    84.8 3747.06    89.2 3740.32    93.7 3736.72   117.8 3725.98   132.7 3714.93
   151.7 3713.05   155.7 3714.09   163.7 3719.29   167.7 3718.92   183.7 3709.29
   190.83706.436   199.7 3705.72  204.87 3706.44   223.8 3712.84   243.8  3715.8
   279.8 3714.24   287.9 3717.44   299.2 3718.81   353.4 3718.67   368.9  3725.7
   394.8 3729.18   423.4 3734.56   431.9 3737.66   453.1 3741.07   546.4 3772.86
#Mann= 5 ,-1,0
       0      .1       0   190.8    .045       0  204.87      .1       0
  210.53     .06       0  300.21      .1       0
Bank Sta=190.8,204.87
XS Rating Curve= 0 ,0
Exp/Cntr(USF)=0,0
Exp/Cntr=0.3,0.1

Type RM Length L Ch R = 1 ,451     ,133.7,134,133.8
XS GIS Cut Line= 4
2272361.43842396556959.7372476762272467.84118258556893.391998184
 2272671.8841197556614.2412314512272620.56043613556318.817101636
#Sta/Elev= 30
       0  3773.4     9.7 3773.71    17.4 3771.42    45.6 3752.23    64.5 3741.82
    88.1 3732.02    99.7 3723.89   134.4 3720.99   209.9 3696.93   260.3 3696.12
   269.3 3697.78   289.2 3695.83   336.1 3697.31   350.73695.592   357.6 3694.94
  365.94 3695.58   427.9 3700.15   472.8 3700.83   516.9 3707.92   529.1 3714.98
   549.4 3709.68   573.7 3710.07   585.9 3716.52   618.4 3725.66   650.9 3728.33
   663.1 3735.86   683.4 3739.27   715.8 3749.76     728 3750.59     771 3763.84
#Mann= 5 ,-1,0
       0      .1       0      40     .06       0  165.39      .1       0
   350.7    .045       0  365.94      .1       0
Bank Sta=350.7,365.94
XS Rating Curve= 0 ,0
Exp/Cntr(USF)=0,0
Exp/Cntr=0.3,0.1

Type RM Length L Ch R = 1 ,317     ,61.8,61.7,61.7
XS GIS Cut Line= 6
2272470.30449824557094.7556483982272614.31379907 557079.93839699
2272670.84181839556869.4617292922272699.70718996556799.703747998
2272890.94027661556566.3753278082272856.22494204556381.040371299
#Sta/Elev= 30
       0 3738.83    13.9 3729.98      34 3729.04    46.1 3723.12    62.2 3719.23
   138.6  3705.9   155.9 3701.78   176.6 3699.25   244.5 3695.58   346.4 3694.13
     363 3699.19   376.7 3693.38   380.3 3693.22   393.3 3696.93   406.3 3693.11
   436.6 3696.08   465.8 3693.33   475.7  3692.3  482.913693.354     510 3697.55
   540.5 3695.97   745.5 3699.89   782.1 3705.78   814.6 3706.71   826.8 3710.25
   847.2 3712.44   879.7 3721.08     892 3722.33   908.2 3731.07   928.7 3733.07
#Mann= 4 ,-1,0
       0     .06       0      20      .1       0   465.8    .045       0
  482.91      .1       0
Bank Sta=465.8,482.91
XS Rating Curve= 0 ,0
Exp/Cntr(USF)=0,0
Exp/Cntr=0.3,0.1

Type RM Length L Ch R = 1 ,255     ,161.3,162.5,157.6
XS GIS Cut Line= 6
2272526.67373906557120.4796720852272670.68303988557105.662420677
 2272727.2110592 556895.185752982272756.07643077556825.427771685
2272947.30951743556592.0993514952272912.59418285556406.764394986
#Sta/Elev= 30
       0 3723.31    45.7  3711.1    96.6 3700.99   110.1 3701.62   138.2 3696.25
   172.5 3693.13   248.8 3692.75   281.9 3694.97   302.7 3690.51   323.4 3689.67
   352.4 3689.68   364.9 3692.96   377.9 3689.27   390.9 3690.45   399.5 3688.03
   453.2 3690.41   459.1 3689.21   475.7  3689.3   500.4 3692.36     550  3693.6
   626.6  3689.6   643.5 3686.88   704.8 3692.73   740.2 3697.61   755.3 3702.28
   789.9 3701.58   816.4  3705.7   840.8 3705.98   881.5 3716.19   928.7 3721.53
#Mann= 3 ,-1,0
       0      .1       0   459.1    .045       0   475.7      .1       0
#XS Ineff= 2 , 0
          391.34 3694.38  584.84         3696.38
Permanent Ineff=
       F       F
Bank Sta=459.1,475.7
XS Rating Curve= 0 ,0
Exp/Cntr(USF)=0,0
Exp/Cntr=0.3,0.1

Type RM Length L Ch R = 1 ,93      ,,,
XS GIS Cut Line= 4
 2272522.9067891557233.8870453632272706.92353285557207.427121424
2273055.71343933556537.5099562382273025.64534394556419.643022327
#Sta/Elev= 30
       0 3728.23    29.6 3715.61      70 3704.98    78.1 3700.52    94.2 3701.56
   154.8 3689.71   185.9 3687.47   203.3 3687.46   215.5 3691.96   233.5 3691.62
   251.6  3687.9   295.3 3691.13   327.9  3689.9   361.9  3691.5   372.4 3690.98
   386.9 3686.22   431.1 3689.09   458.4 3685.86   541.4 3687.43  548.033684.516
   553.3 3682.77   562.7 3684.46   647.7 3687.22   692.7 3685.12   923.5 3686.42
   941.2 3689.41   954.2 3698.42   966.3 3702.71   986.9 3701.42  1062.8 3716.28
#Mann= 4 ,-1,0
       0     .06       0      70      .1       0  548.03    .045       0
   562.7      .1       0
#XS Ineff= 2 , 0
          514.66 3691.38  661.08         3690.95
Permanent Ineff=
       F       F
Bank Sta=548.03,562.7
XS Rating Curve= 0 ,0
Exp/Cntr(USF)=0,0
Exp/Cntr=0.3,0.1
LCMann Table=0

Chan Stop Cuts=-1
Use User Specified Reach Order=0
Composite Channel Slope=5